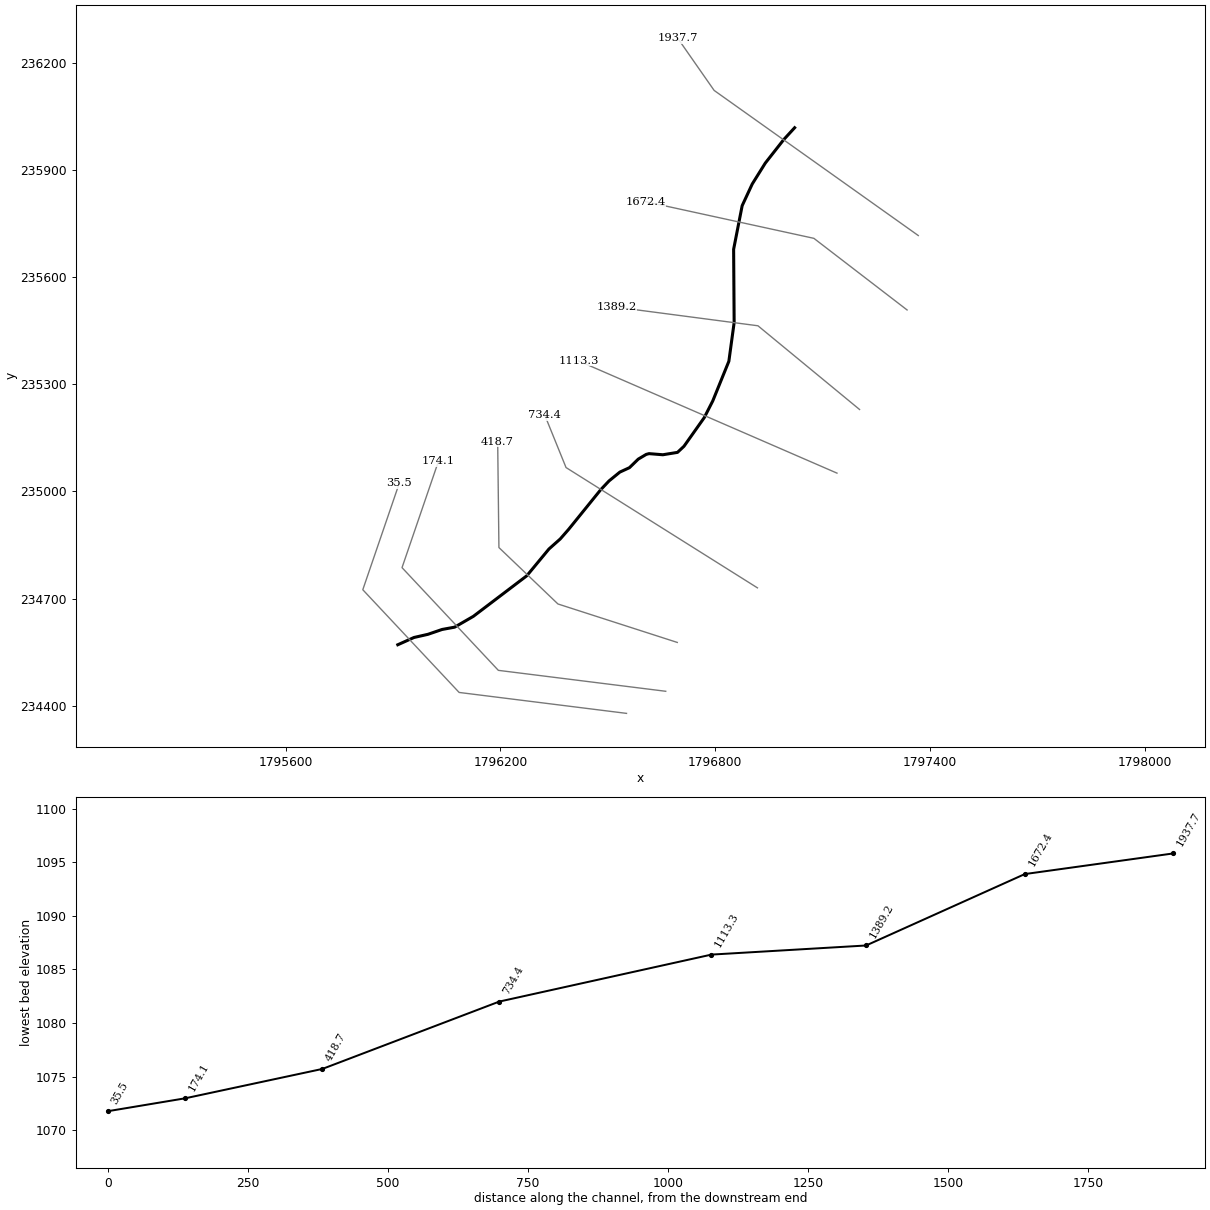
--- SPAWLKRN.prj (project) ---

Proj Title=SPAWLKRN
Current Plan=p01
Geom File=g01
Flow File=f01
Plan File=p01
DSS Export Rating Curves=0
DSS Export Rating Curve Sorted=0
DSS Export Volume Flow Curves=0
DXF OffsetX=0
DXF OffsetY=0
DXF ScaleX=0
DXF ScaleY=0

--- SPAWLKRN.p01 (plan) ---

Plan Title=Floodplain
Program Version=4.00
Geom File=g01
Flow File=f01
K Sum by GR=0
Std Step Tol=0.01
Critical Tol=0.01
Num of Std Step Trials=20
Max Error Tol=0.3
Flow Tol Ratio=0.001
Split Flow NTrial=30
Split Flow Tol=0.02
Split Flow Ratio=0.02
Log Output Level=0
Friction Slope Method=1
Unsteady Friction Slope Method=2
Unsteady Bridges Friction Slope Method=1
Global Log Level=0
CheckData=False
Run HTab=0
Run UNet=0
Run PostProcess=0
UNET Theta=0
UNET Theta Warmup=0
UNET ZTol=0
UNET ZSATol=0
UNET MxIter=0
UNET MaxInSteps=0
UNET DtIC=0
UNET DtMin=0
UNET MaxCRTS=0
UNET WFStab=0
UNET SFStab=0
UNET WFX=0
UNET SFX=0
UNET DSS MLevel=0
UNET DZMax Abort=0
UNET Convert EG Bridges=0
UNET Use Existing IB Tables=0
UNET Froude Limit=0
UNET Froude Power=0
Write IC File=0
Echo Input=False
Echo Output=False
Write Detailed=0

--- SPAWLKRN.f01 (steady flow) ---

Flow Title=NFF Regression Equation
Program Version=4.00
Number of Profiles=1
Profile Names=P100yr
River Rch & RM=SPAWLKRN,Main      ,1937.7
814.2630
River Rch & RM=SPAWLKRN,Main      ,1672.4
972.8919
River Rch & RM=SPAWLKRN,Main      ,734.4
991.3542
River Rch & RM=SPAWLKRN,Main      ,418.7
 999.830
Boundary for River Rch & Prof#=SPAWLKRN,Main      ,1
Up Type=0
Dn Type=3
Dn Slope=0.015467

--- SPAWLKRN.g01 (geometry) ---

Geom Title=USGS 10m DEM
Program Version=4.10

River Reach=SPAWLKRN        ,Main
Reach XY= 30
     1797021.927      236018.301     1796991.396      235984.985
        1796940.      235919.397     1796903.496      235860.794
     1796875.338      235800.061     1796851.479       235678.03
     1796852.925      235472.953     1796838.174      235364.517
     1796793.197      235253.509     1796769.419      235206.755
     1796712.826      235126.598     1796694.655      235109.447
     1796653.776      235102.791     1796615.192      235105.911
     1796607.231       235103.77     1796584.942      235090.493
     1796560.448      235066.618     1796533.617      235054.235
     1796503.346      235029.467     1796479.954        235004.7
     1796390.516      234893.934     1796367.125      234867.103
     1796335.477      234838.895     1796273.559      234763.905
     1796124.266      234650.387     1796071.979      234620.116
      1796036.97      234613.671     1795997.677      234600.164
     1795958.461       234591.22     1795913.251      234570.899

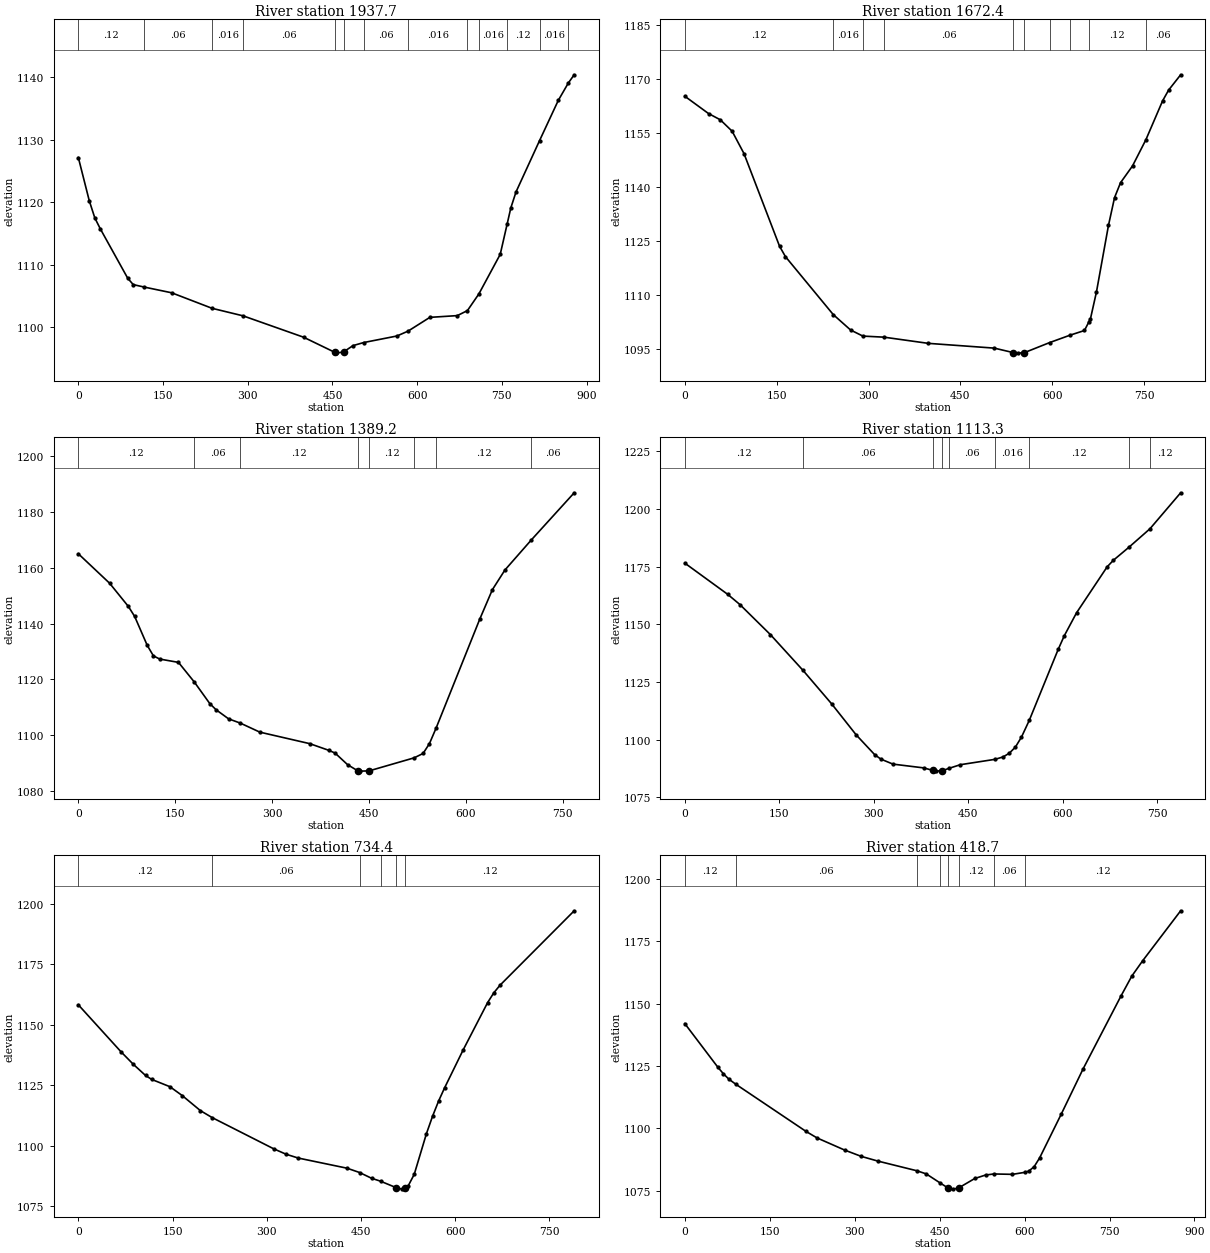
Type RM Length L Ch R = 1 ,1937.7  ,256.2,265.3,274.4
XS GIS Cut Line= 3
     1797367.353      235716.461      1796797.04      236122.711
     1796695.478      236268.544
#Sta/Elev= 30
       0 1127.12    19.4  1120.2    29.2 1117.46    38.9 1115.72    87.5 1107.81
    97.2  1106.8  116.161106.414   165.3 1105.49  236.761103.009  291.771101.801
   398.7 1098.39   454.5 1095.95   457.1 1095.84   469.5 1096.03   486.3 1097.04
  505.271097.533   564.1 1098.58  583.851099.361   622.4 1101.56     671 1101.84
  688.881102.638  709.171105.305     747 1111.64  759.461116.567   765.7 1119.05
     775 1121.63  816.571129.816   849.9 1136.28  867.771139.072   877.9 1140.35
#Mann= 13 ,-1 , 0
       0     .12       0  116.16     .06       0  236.76    .016       0
  291.77     .06       0   454.5    .045       0   469.5     .12       0
  505.27     .06       0  583.85    .016       0  688.88     .06       0
  709.17    .016       0  759.46     .12       0  816.57    .016       0
  867.77     .06       0
Bank Sta=454.5,469.5
XS Rating Curve= 0 ,0
Exp/Cntr=0.3,0.1

Type RM Length L Ch R = 1 ,1672.4  ,281.3,283.3,285.1
XS GIS Cut Line= 3
     1797336.103      235508.128     1797075.686      235708.648
     1796605.799      235811.311
#Sta/Elev= 30
       0 1165.32    38.7 1160.51      58 1158.77    77.3 1155.59    96.7 1149.36
   154.7 1123.63   164.3 1120.74  242.381104.627   270.7 1100.34  290.761098.645
  325.181098.348   397.4 1096.63   505.4  1095.3   536.2 1094.06   544.6 1093.91
   554.4 1094.04  595.86 1096.85  629.051098.899   652.6  1100.2   659.31102.442
   662.4 1103.48   672.2 1110.94   691.8 1129.43   701.7 1137.14   711.5 1141.29
   731.1 1145.96   752.91153.235   780.2 1164.05     790 1167.03   809.6 1171.27
#Mann= 10 ,-1 , 0
       0     .12       0  242.38    .016       0  290.76     .12       0
  325.18     .06       0   536.2    .045       0   554.4     .12       0
  595.86     .06       0  629.05    .016       0   659.3     .12       0
   752.9     .06       0
Bank Sta=536.2,554.4
XS Rating Curve= 0 ,0
Exp/Cntr=0.3,0.1

Type RM Length L Ch R = 1 ,1389.2  ,282.2,275.9,269.6
XS GIS Cut Line= 3
      1797203.29      235229.482     1796919.436      235463.857
     1796523.603       235515.94
#Sta/Elev= 30
       0 1164.95    48.4 1154.42    77.5  1146.1    87.2 1142.54   106.6 1132.22
   116.2 1128.45   125.9 1127.31     155 1126.12  179.641119.059   203.4 1111.41
   213.1  1109.2   232.5 1105.94  250.941104.385   280.9 1101.18   358.4 1097.05
   387.6 1094.68   397.3 1093.71   416.8 1089.53  432.32 1087.38   436.3 1087.24
  449.99 1087.33  519.721091.989   533.6 1093.56   543.4 1097.07  553.87 1102.71
   621.3 1141.58   640.8  1152.1   660.2 1159.13  701.011169.871   767.4 1186.74
#Mann= 8 ,-1 , 0
       0     .12       0  179.64     .06       0  250.94     .12       0
  432.32    .045       0  449.99     .12       0  519.72    .016       0
  553.87     .12       0  701.01     .06       0
Bank Sta=432.32,449.99
XS Rating Curve= 0 ,0
Exp/Cntr=0.3,0.1

Type RM Length L Ch R = 1 ,1113.3  ,381.9,378.9,374.7
XS GIS Cut Line= 2
     1797140.222      235051.349     1796417.999      235365.585
#Sta/Elev= 30
       0 1176.54    68.1 1163.02    87.5 1158.59   136.1 1145.52  187.591130.114
   233.4  1115.5   272.3 1102.08   301.4 1093.59   311.2 1091.63   330.6 1089.43
   379.2  1087.8   394.2 1086.71   398.7 1086.39   409.2 1086.58  419.041087.541
   437.6 1089.17  492.911091.509   505.6 1092.55   515.4 1094.14   525.1 1096.79
   534.8 1101.14  547.241108.432   593.2  1139.2   602.9 1145.11   622.3 1155.02
   670.9 1174.93   680.7 1177.75  705.281183.369  738.831191.404   787.6    1207
#Mann= 9 ,-1 , 0
       0     .12       0  187.59     .06       0   394.2    .045       0
   409.2     .12       0  419.04     .06       0  492.91    .016       0
  547.24     .12       0  705.28     .06       0  738.83     .12       0
Bank Sta=394.2,409.2
XS Rating Curve= 0 ,0
Exp/Cntr=0.3,0.1

Type RM Length L Ch R = 1 ,734.4   ,320.2,315.7,311.1
XS GIS Cut Line= 3
     1796917.999      234730.168     1796383.277      235066.974
     1796324.249      235212.807
#Sta/Elev= 30
       0  1158.3    68.1 1138.81    87.5 1133.68     107 1129.05   116.7 1127.43
   145.8  1124.4   165.3 1120.75   194.4 1114.48   213.11111.605   311.1 1098.68
   330.6 1096.46     350 1094.87   427.8 1090.66  447.651088.883   466.7 1086.51
  481.281085.262   505.6 1082.65   515.3    1082  520.53 1082.62     525  1083.3
   534.7 1088.11   554.2 1105.01   563.9 1112.18   573.6 1118.53   583.3 1124.07
   612.5 1139.58   651.6 1159.25   661.4 1163.27   671.3 1166.42   789.3 1197.21
#Mann= 6 ,-1 , 0
       0     .12       0   213.1     .06       0  447.65    .016       0
  481.28     .12       0   505.6    .045       0  520.53     .12       0
Bank Sta=505.6,520.53
XS Rating Curve= 0 ,0
Exp/Cntr=0.3,0.1

Type RM Length L Ch R = 1 ,418.7   ,245.7,244.6,243.8
XS GIS Cut Line= 4
     1796694.041       234577.39     1796360.708      234685.029
     1796195.777      234843.015     1796192.305       235139.89
#Sta/Elev= 30
       0    1142    58.4 1124.52    68.1 1121.92    77.8 1119.76   89.671117.778
   214.1 1098.82   233.5 1096.22   282.2 1091.36   311.4 1088.84   340.6 1086.96
  410.061083.049   426.4 1081.81  449.861078.335   464.5 1076.21     474 1075.71
   483.5 1076.18   512.1 1079.97   531.1 1081.35  545.691081.781   578.7 1081.63
  600.521082.437   607.4 1082.91     617 1084.72   626.6 1088.21   664.9  1105.8
   703.2 1123.78   770.2 1153.02   789.4 1161.03   808.5 1167.14   875.6 1187.16
#Mann= 8 ,-1 , 0
       0     .12       0   89.67     .06       0  410.06    .016       0
  449.86     .12       0   464.5    .045       0   483.5     .12       0
  545.69     .06       0  600.52     .12       0
Bank Sta=464.5,483.5
XS Rating Curve= 0 ,0
Exp/Cntr=0.3,0.1

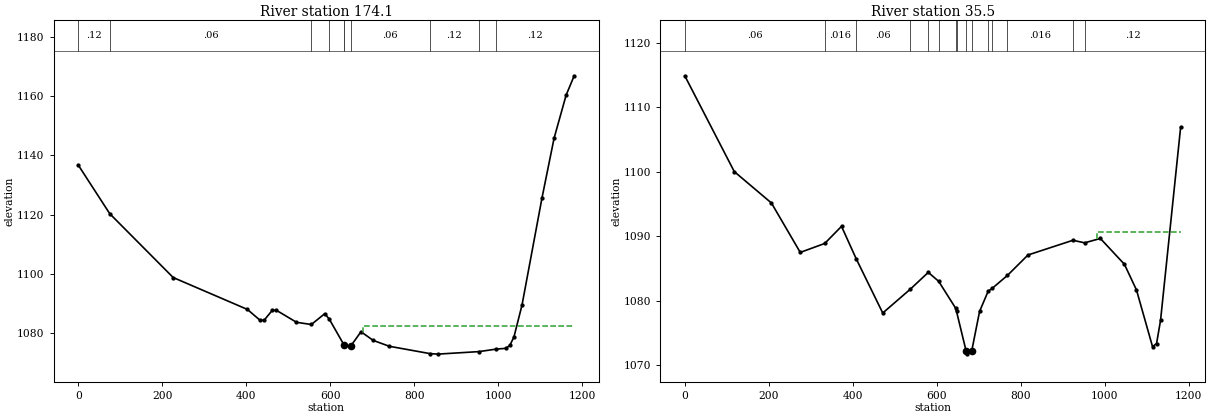
Type RM Length L Ch R = 1 ,174.1   ,137.1,138.6,138.2
XS GIS Cut Line= 4
     1796661.841      234440.636     1796194.176       234499.23
     1795925.079      234786.773     1796027.075      235085.168
#Sta/Elev= 30
       0 1136.65   74.841120.296   225.8 1098.79   402.6 1088.03     432 1084.46
   441.9 1084.32   461.5 1087.69   471.3 1087.77   519.4  1083.7  554.811082.956
   586.6 1086.59  597.261084.825  633.121075.918   633.2  1075.9   648.2 1075.61
     673 1080.52   701.8 1077.61   740.3 1075.62  836.821073.151   855.5 1072.97
  953.721073.819  994.921074.659    1018 1074.92  1027.6 1075.96  1037.2 1078.79
  1056.3 1089.48    1104 1125.67  1132.7 1145.74  1161.4 1160.27  1180.5 1166.77
#Mann= 10 ,-1 , 0
       0     .12       0   74.84     .06       0  554.81    .016       0
  597.26     .06       0  633.12     .12       0   633.2    .045       0
   648.2     .06       0  836.82     .12       0  953.72     .06       0
  994.92     .12       0
#XS Ineff= 2 , 0
                           677.4          1082.5
Permanent Ineff=
       F       F
Bank Sta=633.2,648.2
XS Rating Curve= 0 ,0
Exp/Cntr=0.3,0.1

Type RM Length L Ch R = 1 ,35.5    ,42.8,35.5,28.9
XS GIS Cut Line= 4
     1796552.249      234378.787     1796084.584      234437.381
     1795815.486      234724.924     1795917.483      235023.319
#Sta/Elev= 30
       0 1114.88   117.8 1100.04   206.2 1095.18   274.9 1087.52  333.161088.907
   373.1 1091.56  408.021086.541   471.3 1078.13  536.651081.806   579.71084.427
  604.441083.043  644.741078.885  646.921078.378  669.58  1072.3     673 1071.76
  683.27  1072.3   701.8 1078.37  722.311081.514  731.87 1081.95  768.031083.949
   817.1 1087.12  924.08  1089.4  951.891089.004   989.4 1089.68  1046.7 1085.68
  1075.4  1081.7  1113.6 1072.92  1123.2  1073.4  1132.7 1076.99  1180.5  1106.9
#Mann= 15 ,-1 , 0
       0     .06       0  333.16    .016       0  408.02     .06       0
  536.65    .016       0   579.7     .08       0  604.44     .06       0
  644.74     .08       0  646.92     .06       0  669.58    .045       0
  683.27     .06       0  722.31    .016       0  731.87     .08       0
  768.03    .016       0  924.08     .08       0  951.89     .12       0
#XS Ineff= 2 , 0
                           980.8         1090.61
Permanent Ineff=
       F       F
Bank Sta=669.58,683.27
XS Rating Curve= 0 ,0
Exp/Cntr=0.3,0.1

Chan Stop Cuts=-1
Use User Specified Reach Order=0
Composite Channel Slope=5